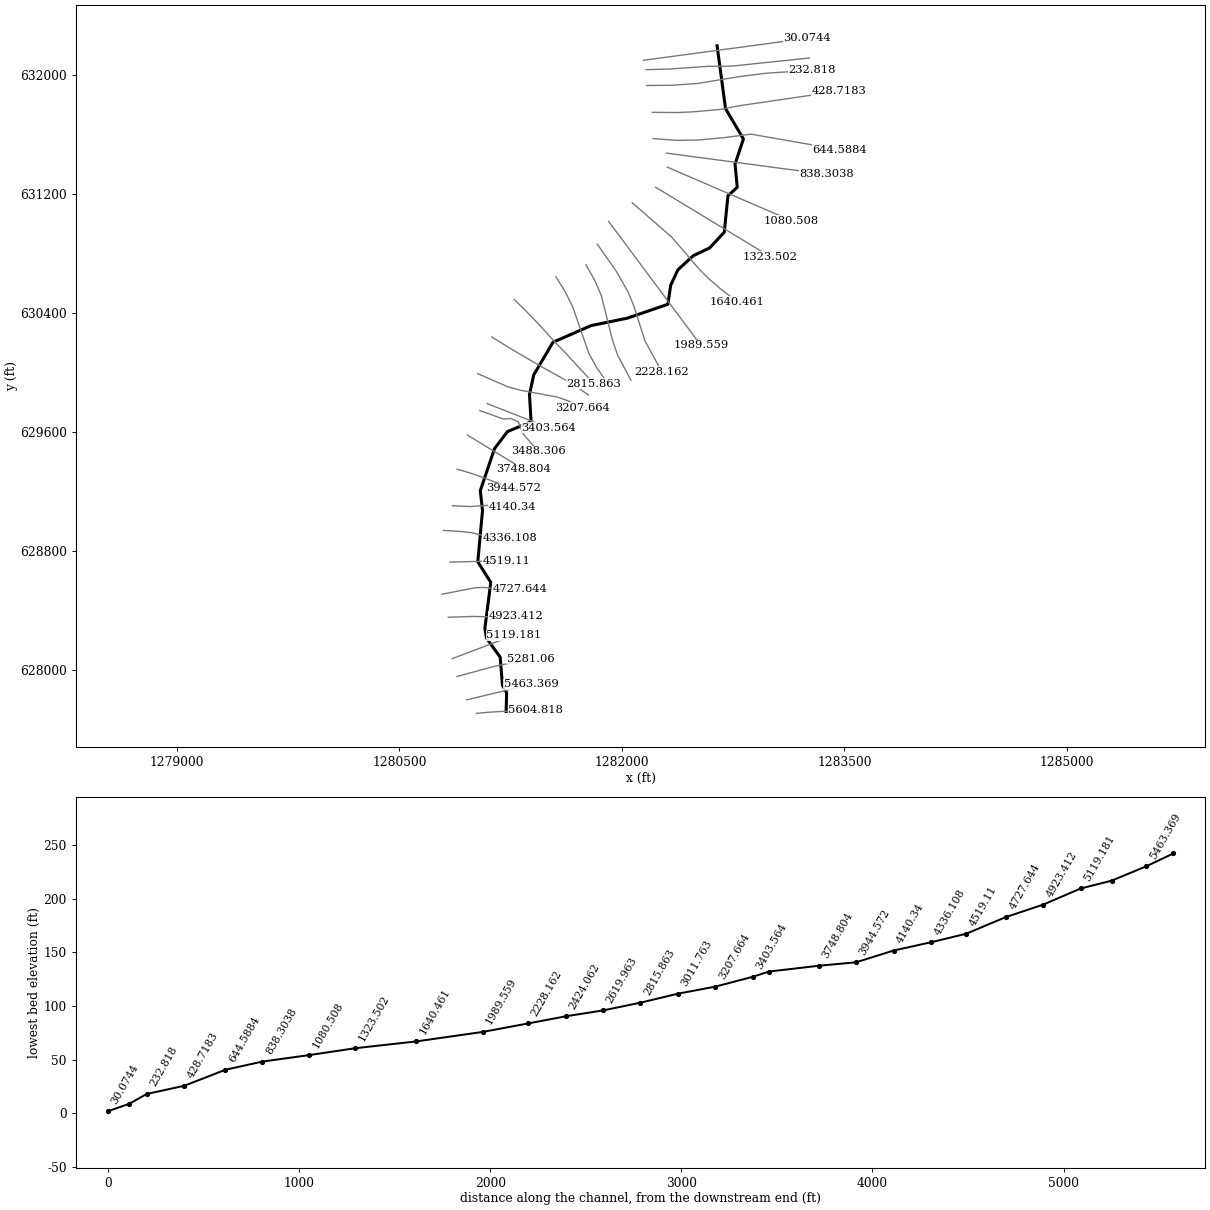
--- 763_ras.prj (project) ---

Proj Title=763
Current Plan=p01
Default Exp/Contr=0.3,0.1
English Units
Geom File=g01
Flow File=f01
Plan File=p01
Y Axis Title=Elevation
X Axis Title(PF)=Main Channel Distance
X Axis Title(XS)=Station
BEGIN DESCRIPTION:
RFD model 763 exported to HEC-RAS
END DESCRIPTION:

--- 763_ras.p01 (plan) ---

Plan Title=Plan 01
Program Version=4.10
Short Identifier=Plan 01
Geom File=g01
Flow File=f01
Subcritical Flow
Calc Critical at every XS
Secant Critical Depth

--- 763_ras.f01 (steady flow) ---

Flow Title=Flow 01
Program Version=5.01
Number of Profiles= 5
Profile Names=10yr,25yr,50yr,100yr,500yr
River Rch & RM=763,29,5604.818
  426.64  516.86  618.35  669.94   801.5
River Rch & RM=763,29,5463.369
  473.07  581.83  698.47   768.4  937.48
River Rch & RM=763,29, 5281.06
  483.17  596.09   716.1  790.25  968.02
River Rch & RM=763,29,5119.181
   488.1  603.07  724.72  800.98  983.05
River Rch & RM=763,29,4923.412
   550.9  692.81  835.91  940.55 1181.16
River Rch & RM=763,29,4727.644
  565.83  714.38   862.7  974.54 1230.07
River Rch & RM=763,29, 4519.11
  580.65  735.86  889.41 1008.56 1279.28
River Rch & RM=763,29,4336.108
  599.85  763.82  924.19 1053.06 1343.99
River Rch & RM=763,29, 4140.34
  609.11  777.34  941.04 1074.68 1375.58
River Rch & RM=763,29,3944.572
   620.7  794.32  962.19 1101.92 1415.49
River Rch & RM=763,29,3748.804
  629.91  807.84  979.05 1123.66 1447.46
River Rch & RM=763,29,3488.306
  634.85   815.1   988.1 1135.36  1464.7
River Rch & RM=763,29,3403.564
  640.53  823.47  998.54 1148.88 1484.64
River Rch & RM=763,29,3207.664
  644.54  829.39 1005.93 1158.44 1498.78
River Rch & RM=763,29,3011.763
  651.28  839.33 1018.34 1174.54  1522.6
River Rch & RM=763,29,2815.863
  667.11  862.75 1047.58 1212.56 1579.07
River Rch & RM=763,29,2619.963
   673.5  872.23 1059.43 1228.02 1602.09
River Rch & RM=763,29,2424.062
  712.46  930.31 1132.08 1323.19 1744.77
River Rch & RM=763,29,2228.162
  713.49  931.84    1134 1325.72 1748.58
River Rch & RM=763,29,1989.559
  731.59     959 1168.02 1370.55 1816.34
River Rch & RM=763,29,1640.461
   735.2  964.41 1174.81 1379.52 1829.93
River Rch & RM=763,29,1323.502
  786.61 1042.09 1272.29    1509 2027.51
River Rch & RM=763,29,1080.508
  791.01 1048.77 1280.68  1520.2 2044.73
River Rch & RM=763,29,838.3038
  798.25 1059.79 1294.52 1538.71 2073.21
River Rch & RM=763,29,644.5884
  821.06 1094.57 1338.26 1597.34 2163.74
River Rch & RM=763,29,428.7183
  826.82 1103.37 1349.33 1612.23  2186.8
River Rch & RM=763,29, 232.818
  830.08 1108.37 1355.62 1620.68  2199.9
River Rch & RM=763,29,140.4436
  830.62  1109.2 1356.66 1622.08 2202.08
River Rch & RM=763,29, 30.0744
  833.32 1113.33 1361.86 1629.09 2212.95
Boundary for River Rch & Prof#=763,29,1
Up Type= 0
Dn Type= 2
Boundary for River Rch & Prof#=763,29,2
Up Type= 0
Dn Type= 2
Boundary for River Rch & Prof#=763,29,2
Up Type= 0
Dn Type= 2
Boundary for River Rch & Prof#=763,29,2
Up Type= 0
Dn Type= 2
Boundary for River Rch & Prof#=763,29,2
Up Type= 0
Dn Type= 2

--- 763_ras.g01 (geometry) ---

Geom Title=763
Program Version=4.10

River Reach=763,29
Reach XY= 30
 1281219.2952828627720.6746867541281222.62861887627845.674649528
 1281194.5954655627896.576785196 1281179.2235252628085.922511786
1281086.99262244628213.9607062041281076.14192802628280.149942324
1281115.76866412628589.6117478761281028.26866412628727.806192324
1281060.12870288629073.1742898891281045.12871119629206.507584078
1281140.96202456629489.0074974031281228.46200212629604.007460681
1281387.62862373629669.8407698281281376.79529905629853.174049033
1281405.12862788629984.840675801  1281535.128596630204.840606652
1281792.62852333630317.340565705 1282037.6284525630367.340543677
1282310.12837483630460.6738412771282328.46170649630587.340469789
1282376.79502859630691.5071041361282480.96166735630787.340405943
1282591.79496953630839.8403871371282690.12827698630945.673686125
1282715.12827687631191.5069457881282777.62826005631247.340260699
1282762.81727523631403.8044562191282819.24088633631573.075289547
1282698.63973085631777.1535838411282641.79499481632199.839981937

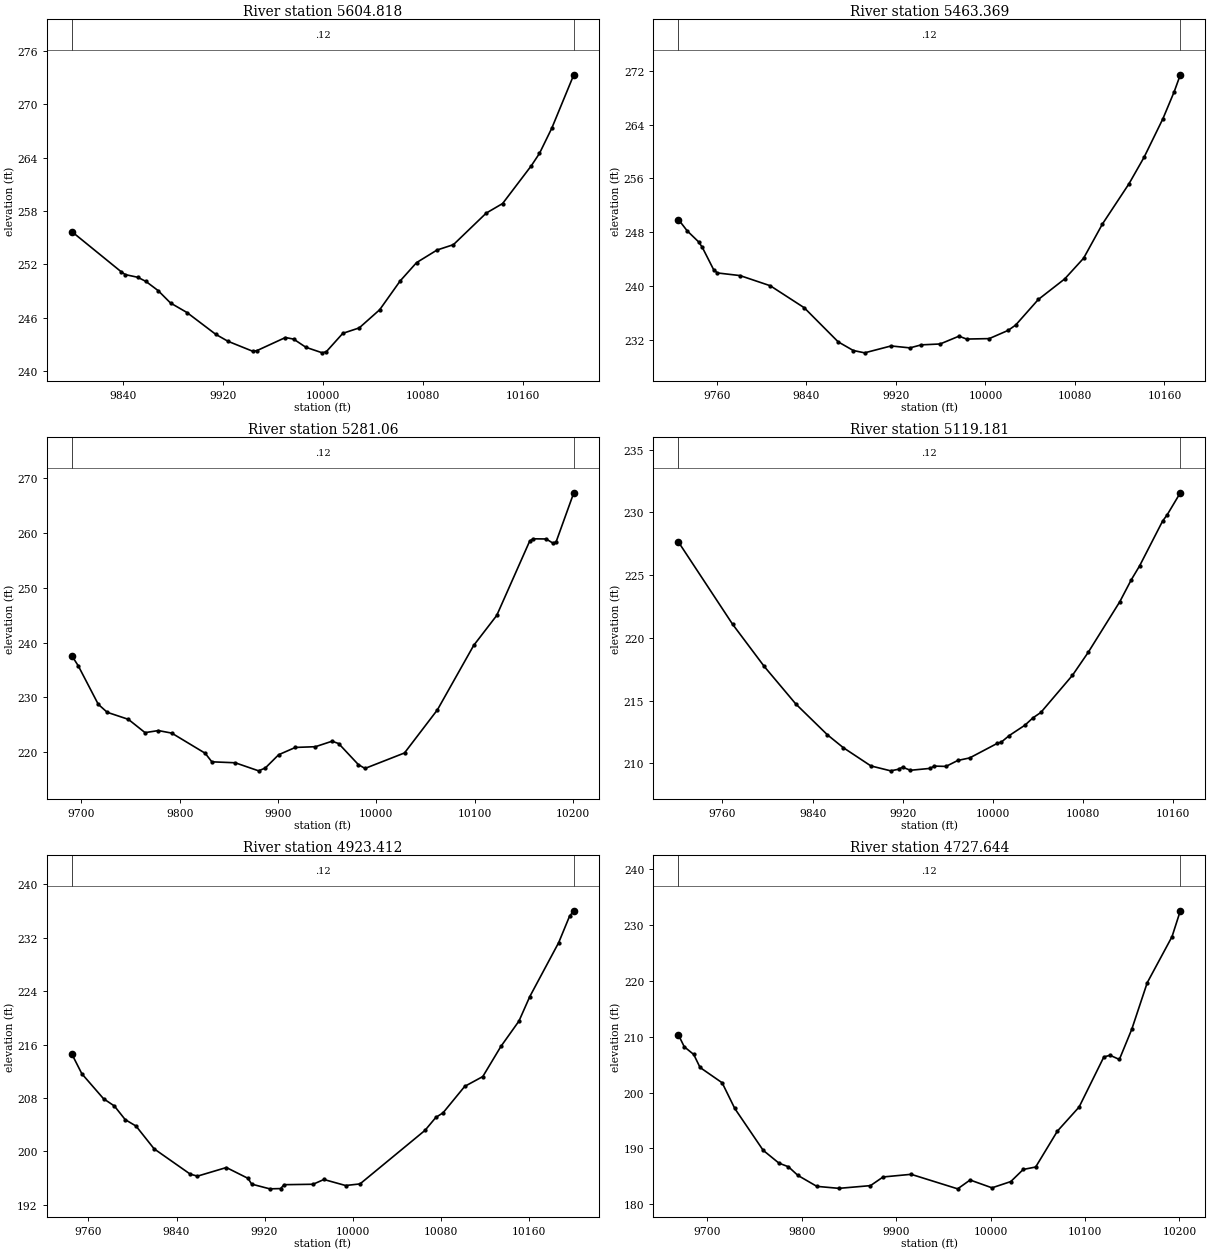
Type RM Length L Ch R = 1 ,5604.818,141.448800,141.448800,141.448800
XS GIS Cut Line= 6
1281018.79842653627707.7147352131281102.81366313627715.451326755
1281169.26836245627719.655608913  1281218.264536627721.642964109
1281220.26356015627721.7054335531281420.17990931627727.391738544
#Sta/Elev= 30
9799.005255.6676 9838.44251.16769841.735250.84549851.619250.54879858.208250.0851
9868.092249.04229877.976247.65229891.138246.5831 9914.15244.13489924.012243.3474
9943.736242.23169947.024242.28849970.012243.77199976.579 243.593 9986.43242.6712
9999.564242.048910002.85242.190710015.97244.2411 10029.1244.851210045.51246.8952
10061.92250.136210075.05252.194410091.46  253.6110104.59254.213210130.85257.7616
10143.98258.837510166.95263.081910173.52264.480110183.36267.3066   10201273.3161
#Mann= 3 , 0 , 0
9799.005    0.12       09799.005    0.12       0   10201    0.12       0
#XS Ineff= 2 , 0
       09962.814                       0
Bank Sta=9799.005,10201
Exp/Cntr=0.3,0.1

Type RM Length L Ch R = 1 ,5463.369,182.309600,182.309600,182.309600
XS GIS Cut Line= 2
1280952.07219422 627798.144734011281388.18330532  627903.0058451
#Sta/Elev= 30
9725.673   249.99733.459 248.2259743.582246.60329746.956245.77979757.079242.4664
9760.453241.97419780.699241.58249807.694 240.0749838.063236.80939868.432231.7404
 9881.93230.45819892.053230.11199915.673231.13459932.545230.84849942.668 231.296
9959.539231.42799976.411232.5883 9983.16232.157910003.41232.224510020.28233.4416
10027.03234.234110047.27238.031610070.89241.087410087.76244.159310104.64249.2516
10128.26255.196110141.75259.130410158.63264.862710168.75268.887610174.21271.3952
#Mann= 3 , 0 , 0
9725.673    0.12       09725.673    0.12       010174.21    0.12       0
#XS Ineff= 2 , 0
       09942.243                       0
Bank Sta=9725.673,10174.21
Exp/Cntr=0.3,0.1

Type RM Length L Ch R = 1 , 5281.06,161.879200,161.879200,161.879200
XS GIS Cut Line= 5
1280887.85344419627955.8877895471281142.73232397628024.777382866
1281186.40059116628033.7157616911281188.37643024628034.025697216
1281384.18168917 628074.72072944
#Sta/Elev= 30
9690.402237.56139696.795235.77379717.186228.75749726.306227.30259747.773226.0256
9764.766223.6048 9778.36223.97849791.955223.5158 9825.94219.85249832.737218.2927
9856.527218.11799880.317216.65059887.114217.16579900.708219.58259917.701 220.911
9938.093221.04259955.076222.04179961.774221.61239981.867217.77499988.564 217.089
10028.75219.904610062.26227.760510099.12239.472210122.58244.930210156.09258.4531
10159.44258.881310172.84258.849810179.54258.119710182.89258.266410200.99267.2566
#Mann= 3 , 0 , 0
9690.402    0.12       09690.402    0.12       010200.99    0.12       0
#XS Ineff= 2 , 0
       0 9962.54                       0
Bank Sta=9690.402,10200.99
Exp/Cntr=0.3,0.1

Type RM Length L Ch R = 1 ,5119.181,195.768100,195.768100,195.768100
XS GIS Cut Line= 2
1280855.65581691628075.9398728761281272.32248357628233.274942324
#Sta/Elev= 30
9720.984 227.6319769.011221.08239797.067217.72229825.122214.72679853.178212.2692
9867.206211.24949891.754209.79079909.289209.39889916.303209.5261 9919.81209.6911
9926.824209.44339944.358209.59429947.865209.77729958.386209.75219968.907210.2268
9979.428210.428810003.98211.591810007.48211.6875 10014.5212.208210028.52 213.041
10035.54213.619210042.55214.048610070.61 217.00810084.64218.845410112.69222.8834
10122.79 224.61710130.23225.734710150.65229.305410154.77229.812210166.37231.5596
#Mann= 3 , 0 , 0
9720.984    0.12       09720.984    0.12       010166.37    0.12       0
#XS Ineff= 2 , 0
       0 9962.33        10038.02       0
Bank Sta=9720.984,10166.37
Exp/Cntr=0.3,0.1

Type RM Length L Ch R = 1 ,4923.412,195.768100,195.768100,195.768100
XS GIS Cut Line= 6
1280829.25969419628354.3252895471280989.86241034628359.875972748
1281083.14205983628358.0145450531281085.14037308628357.932422593
1281190.23282194 628356.240902961281285.01063025628360.432194307
#Sta/Elev= 30
9745.003214.5571    9754211.63049773.697207.89079783.545206.80319793.393204.7593
9803.242203.79259819.656200.38349852.484196.58979859.049196.28999885.312197.5799
9905.008195.9563 9908.29195.09459924.698194.38779934.542194.42659937.824195.0086
9964.075195.0736 9973.92195.78749993.609194.886310006.74195.1249 10065.8203.1516
10075.64205.0917 10082.2205.780510101.89209.741910118.31211.213810134.73215.7213
10151.15219.5236   10161 223.19510187.27231.287310197.13235.241110200.98236.0508
#Mann= 3 , 0 , 0
9745.003    0.12       09745.003    0.12       010200.98    0.12       0
#XS Ineff= 2 , 0
       09887.668        10065.34       0
Bank Sta=9745.003,10200.98
Exp/Cntr=0.3,0.1

Type RM Length L Ch R = 1 ,4727.644,208.534100,208.534100,208.534100
XS GIS Cut Line= 6
1280786.29094422628509.2732062191281006.84459627628552.408161297
1281057.71916917628555.1254529511281086.45894337628553.888805345
1281183.97606644628543.0530476421281312.90856063 628544.23985599
#Sta/Elev= 30
9669.398210.3024 9675.54208.19439685.569206.81749692.255204.49169715.656201.7521
9729.028197.14899759.115189.6598 9775.83187.36449785.859186.71459795.888185.1703
9815.946183.20689839.347182.85089872.777183.33789886.149184.88949915.855185.3628
9965.128182.7628  9978.3 184.34410001.49182.945110021.37184.061510034.59186.2352
10047.75186.668410070.77193.098310093.75197.407910119.99206.375710126.56206.6757
 10136.4205.922110149.53 211.32110165.94219.6697 10192.2227.914110200.98232.5434
#Mann= 3 , 0 , 0
9669.398    0.12       09669.398    0.12       010200.98    0.12       0
#XS Ineff= 2 , 0
       09955.035                       0
Bank Sta=9669.398,10200.98
Exp/Cntr=0.3,0.1

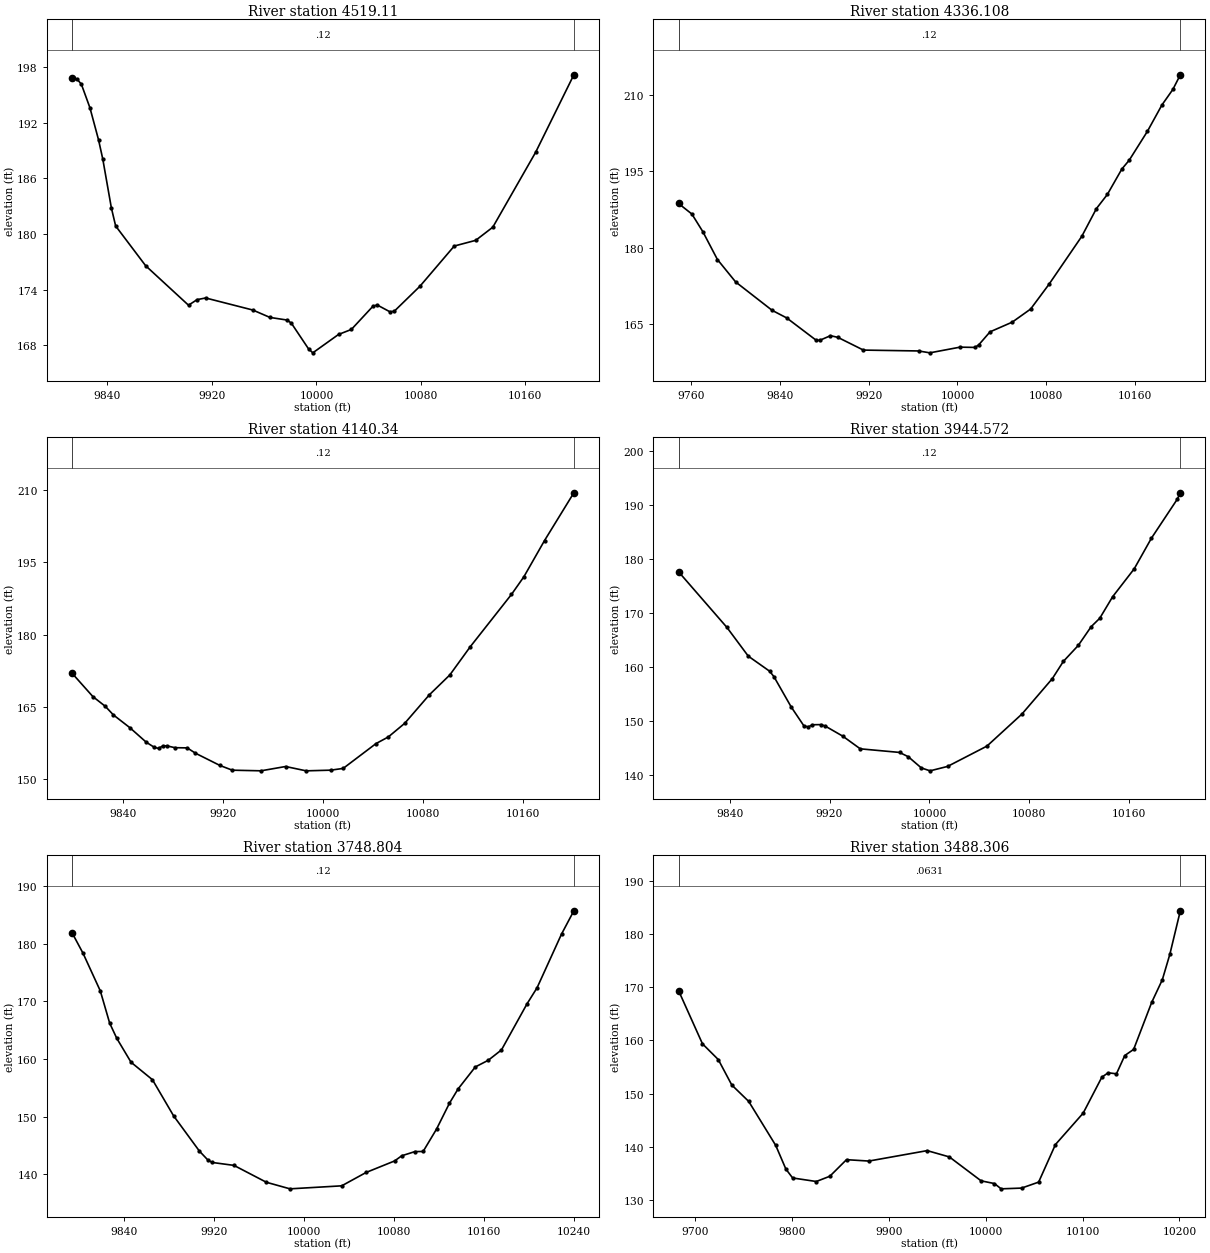
Type RM Length L Ch R = 1 , 4519.11,183.002000,183.002000,183.002000
XS GIS Cut Line= 2
1280840.97844419628725.4190395471281225.09302753628735.835706219
#Sta/Elev= 30
9812.881196.84459816.717 196.6859819.999196.14159826.563193.60189833.127190.1622
9836.409188.06859842.973182.81389846.255180.86389869.229176.5798 9902.05172.3257
9908.614172.92629915.178173.1051 9951.28171.80619964.408171.00969977.536170.7258
9980.818170.38769993.947167.62479997.229167.193110016.92169.172910026.77169.7138
10043.18172.199610046.46172.356210056.31171.614710059.59171.673610079.28174.3704
10105.54178.701210121.95179.314610135.07 180.73310167.89188.810210197.14197.1576
#Mann= 3 , 0 , 0
9812.881    0.12       09812.881    0.12       010197.14    0.12       0
#XS Ineff= 2 , 0
       09945.017                       0
Bank Sta=9812.881,10197.14
Exp/Cntr=0.3,0.1

Type RM Length L Ch R = 1 ,4336.108,195.768000,195.768000,195.768000
XS GIS Cut Line= 6
1280796.70761088628938.9607062341280920.86327597628930.827033505
1280983.96588412628924.0329857771281075.83731827628902.541595876
1281115.75339797628896.0018933861281245.24286196628888.799605787
#Sta/Elev= 30
9748.474188.67179760.515186.59659770.379183.1369 9783.53177.6667 9799.97173.2579
9832.848167.6836    9846166.19279872.303161.8524  9875.6161.7739  9885.5162.7015
9892.099162.37759915.198159.87379965.007159.70339975.089159.333310002.26 160.449
10015.82160.398210019.21160.906710029.38 163.45910049.35165.358410065.98167.9362
10082.49172.782710112.12182.221610125.29187.663110135.14190.435910148.27195.4492
10154.84197.157810171.25202.830610184.38208.021710194.23211.068210200.97213.9524
#Mann= 3 , 0 , 0
9748.474    0.12       09748.474    0.12       010200.97    0.12       0
#XS Ineff= 2 , 0
       09895.762                       0
Bank Sta=9748.474,10200.97
Exp/Cntr=0.3,0.1

Type RM Length L Ch R = 1 , 4140.34,195.768100,195.768100,195.768100
XS GIS Cut Line= 6
 1280857.6660977629104.4689386031280980.12534925629099.807588889
1281084.39559277 629107.052032871281131.01011917629107.883672275
1281186.31030729 629104.85883113 1281258.5766107629096.062485093
#Sta/Elev= 30
9799.021 171.9439815.723167.07429825.582165.07049832.155 163.262  9845.3160.6143
9858.445157.58719865.018156.50389868.304156.30239871.585156.79769874.866156.8318
9881.428156.45029891.272156.40669897.834155.3022 9917.52152.74449927.368151.7662
9950.355151.63749970.058152.53299986.534151.631410006.31151.772110016.19152.1397
10042.48157.304610052.33158.683210065.45161.516810085.16167.440310101.59171.5825
10118.01177.4711   10151188.352610160.92192.018510177.45199.552310200.96209.4999
#Mann= 3 , 0 , 0
9799.021    0.12       09799.021    0.12       010200.96    0.12       0
#XS Ineff= 2 , 0
       09891.943                       0
Bank Sta=9799.021,10200.96
Exp/Cntr=0.3,0.1

Type RM Length L Ch R = 1 ,3944.572,195.768000,195.768000,195.768000
XS GIS Cut Line= 6
1280889.75227207 629351.165594611281000.63484488629317.645852551
1281079.60665431629288.6082821381281081.48904363629287.932552575
1281162.79945309629257.361627752 1281270.3445608629222.276514627
#Sta/Elev= 30
9799.021177.61399837.759167.30269854.897161.96899872.034159.17059875.461158.1604
9889.171152.58879899.454149.04269902.881148.85249906.309 149.2529913.163149.2812
9916.625148.99519930.608147.1335 9944.59144.7897 9976.05144.12229983.042143.3275
9993.528141.248510000.52140.709110014.53141.526510046.08145.294410074.12151.2399
10098.49157.811410107.27160.990410119.19 163.94410129.55167.429810136.45168.9917
 10146.8172.996410164.06178.160910177.86183.845410198.57191.069810200.99192.2528
#Mann= 3 , 0 , 0
9799.021    0.12       09799.021    0.12       010200.99    0.12       0
#XS Ineff= 2 , 0
       09904.969                       0
Bank Sta=9799.021,10200.99
Exp/Cntr=0.3,0.1

Type RM Length L Ch R = 1 ,3748.804,260.498500,260.498500,260.498500
XS GIS Cut Line= 2
1280957.82595578629580.352488622 1281339.7704002 629349.23269695
#Sta/Elev= 30
 9793.78181.90689803.572  178.349818.911171.81879827.255166.21829833.593163.5798
9846.267159.44129865.279156.41749884.101150.1474 9907.11144.01829914.779142.4468
9918.614142.05319937.788141.55129966.674138.61929987.639137.480910033.66138.0023
 10055.4140.323610080.74142.321710087.08143.219510098.85143.945310106.09 143.961
10118.02147.839610129.52152.332910137.19154.808710152.53158.629410164.04159.7854
 10175.8161.582410198.55169.580310207.49172.369810229.23181.678810240.21185.7251
#Mann= 3 , 0 , 0
 9793.78    0.12       0 9793.78    0.12       010240.21    0.12       0
#XS Ineff= 2 , 0
       09935.538                       0
Bank Sta=9793.78,10240.21
Exp/Cntr=0.3,0.1

Type RM Length L Ch R = 1 ,3488.306,84.741800,84.741800,84.741800
XS GIS Cut Line= 6
1281042.46137244629745.2830441891281201.96658075629687.774363637
1281250.79470575629692.1146413981281301.80240342629668.755907461
1281335.92749852629586.691563725 1281435.4327566629470.079995379
#Sta/Elev= 30
9683.182169.36029707.881159.34329724.184156.38549738.134 151.5979755.572148.5191
9783.473140.23999793.935 135.7919800.911134.12029825.323133.45479839.274134.4411
9856.491137.55929879.547137.29849939.724139.26099962.605138.07679995.342133.5807
10009.16133.066310016.03132.074910037.11132.215110054.72133.339110072.06140.4041
10100.68146.311710119.95153.070510126.44153.896810135.03153.707810143.61157.1444
10152.76158.296610171.41167.149910182.35 171.39310190.06176.143910200.92184.3612
#Mann= 3 , 0 , 0
9683.182  0.0631       09683.182  0.0631       010200.92  0.0631       0
#XS Ineff= 2 , 0
       09971.348                       0
Bank Sta=9683.182,10200.92
Exp/Cntr=0.3,0.1

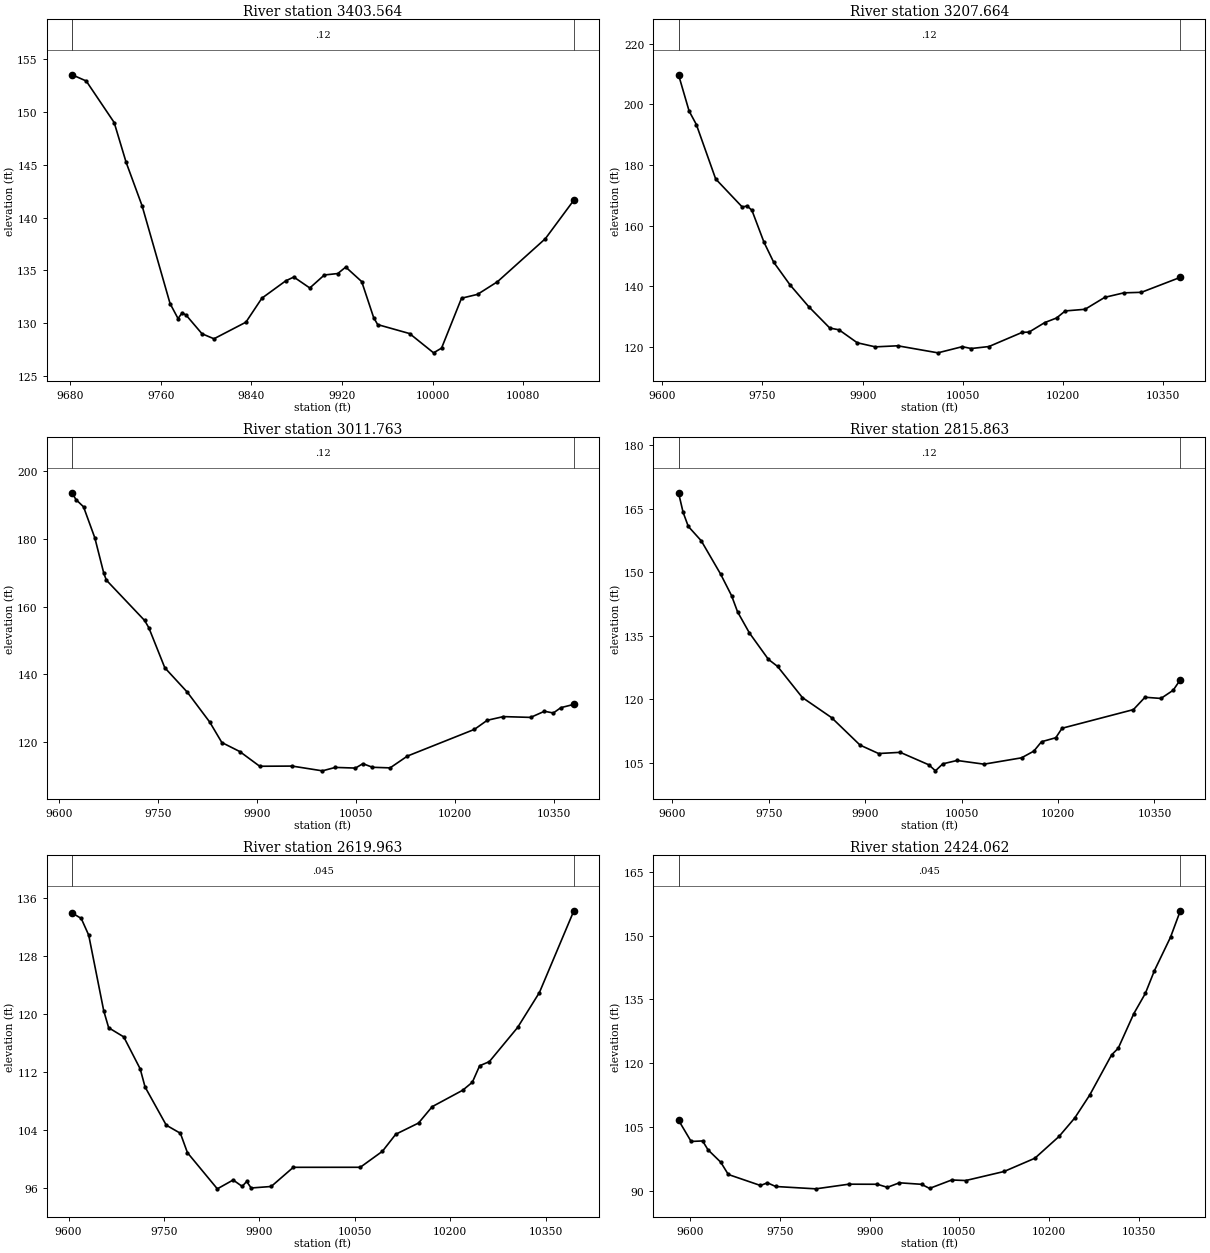
Type RM Length L Ch R = 1 ,3403.564,195.900300,195.900300,195.900300
XS GIS Cut Line= 2
1281092.37456691629791.9410302791281504.70095578629630.265683055
#Sta/Elev= 30
9681.686153.50589694.172152.9191 9718.84148.99029729.412145.21889743.508141.1022
9768.176131.85989775.224130.43839778.749130.97289782.273130.77479796.369129.0007
9806.941128.52629835.133130.09629849.229132.36729870.373134.01539877.421134.3663
9891.517133.33249904.347134.56269916.186134.69839923.234135.3095 9937.33133.9363
9947.902130.52279951.426129.86839979.618129.018610000.76127.195810007.81127.6437
10025.43132.364710039.53132.727310057.15133.923810099.44137.999210124.58141.6435
#Mann= 3 , 0 , 0
9681.686    0.12       09681.686    0.12       010124.58    0.12       0
#XS Ineff= 2 , 0
       09938.617                       0
Bank Sta=9681.686,10124.58
Exp/Cntr=0.3,0.1

Type RM Length L Ch R = 1 ,3207.664,195.900200,195.900200,195.900200
XS GIS Cut Line= 6
1281027.32165084629993.4306376891281232.93567333629904.537780953
1281315.59951137629882.439529607 1281564.2915832629836.260548761
1281645.81614463629807.728568092 1281737.2650861629762.608224524
#Sta/Elev= 30
9624.378209.78319640.189197.8237 9651.04193.37459679.977175.41429719.764166.1594
9726.998166.50659734.232165.08149752.318154.52769766.663148.00959791.263140.4719
9819.361 133.2599850.908  126.219864.595125.64619891.968121.36449918.969120.0166
9952.513120.368810012.67118.044310049.22120.078610062.49119.467310089.04120.1207
10138.99124.8097 10149.1 124.883 10172.7128.0339 10190.3129.538310203.35131.8726
10232.98132.411910262.55136.360710291.14 137.83810317.37138.012810375.62142.9542
#Mann= 3 , 0 , 0
9624.378    0.12       09624.378    0.12       010375.62    0.12       0
#XS Ineff= 2 , 0
       09946.252                       0
Bank Sta=9624.378,10375.62
Exp/Cntr=0.3,0.1

Type RM Length L Ch R = 1 ,3011.763,195.900300,195.900300,195.900300
XS GIS Cut Line= 6
1281122.01213093630240.4705528751281249.14642148630162.648294044
1281477.12070881630029.4190362321281638.57775719629940.286924289
1281699.38256258629902.2859256251281773.68561938 629850.30468521
#Sta/Elev= 30
9619.966193.63999625.773191.64659637.313189.49669654.446180.30649668.086169.8061
9671.933167.81049729.856155.8896 9736.14153.78879760.407141.92579794.571 134.691
9828.583125.83249846.808119.82369873.933117.15919904.166112.80829953.295112.8605
9999.052111.452810018.78112.4668 10049.2 112.26910060.45113.5725   10075112.5024
10101.67112.3274 10127.9115.820210229.46123.7159 10248.8126.397310273.28127.4804
10314.55127.248610335.47129.062510348.89128.549510360.34130.1274   10380131.0987
#Mann= 3 , 0 , 0
9619.966    0.12       09619.966    0.12       0   10380    0.12       0
#XS Ineff= 2 , 0
       09938.819         10077.8       0
Bank Sta=9619.966,10380
Exp/Cntr=0.3,0.1

Type RM Length L Ch R = 1 ,2815.863,195.900300,195.900300,195.900300
XS GIS Cut Line= 6
1281273.56432376 630493.111713771281341.41599639630427.350091989
1281429.48003051630336.6968591621281557.06246623630196.852931503
1281617.26175088630135.1507274961281810.51714637629926.791482477
#Sta/Elev= 30
 9609.69168.78399616.723164.20789624.842160.84419645.008157.4477  9675.1149.5869
9692.149144.49889701.577140.64239719.951135.67049749.547129.42489763.673127.7814
9802.283120.4211  9847.7115.67889892.056109.17949920.895107.18859954.541107.4695
9999.206104.513410009.33103.099210020.78104.751410042.95105.548410084.95104.6744
 10143.3106.173210162.44107.760210174.35109.974410196.57110.920210206.32113.1618
10317.33117.564710335.36120.484410360.13120.200910379.15122.130810390.31124.6203
#Mann= 3 , 0 , 0
 9609.69    0.12       0 9609.69    0.12       010390.31    0.12       0
#XS Ineff= 2 , 0
       09953.606        10062.55       0
Bank Sta=9609.69,10390.31
Exp/Cntr=0.3,0.1

Type RM Length L Ch R = 1 ,2619.963,195.900300,195.900300,195.900300
XS GIS Cut Line= 6
1281555.72293252630644.6297769051281617.77947337630544.870209512
1281669.17821274630440.7204264221281777.59331997630128.648337958
 1281827.5228306630038.2185169181281897.10273235629939.474642777
#Sta/Elev= 30
 9605.55133.9205 9619.96133.16519631.723130.86179655.356120.42379663.093118.0963
9686.801116.83879712.675112.42469720.285109.9374 9753.65104.6694 9775.84103.5531
9786.936100.87449833.91795.894579858.80397.114919872.96596.231189880.04696.91175
9887.12896.011539918.62596.21911 9953.3798.8615310058.6698.8656610093.42101.0668
10114.44103.420210150.21104.961710171.75107.222810219.79109.491210234.84110.5887
10246.29112.858610261.55113.426210306.01 118.13810340.29122.955710394.44134.2218
#Mann= 3 , 0 , 0
 9605.55   0.045       0 9605.55   0.045       010394.44   0.045       0
#XS Ineff= 2 , 0
       09930.575        10072.42       0
Bank Sta=9605.55,10394.44
Exp/Cntr=0.3,0.1

Type RM Length L Ch R = 1 ,2424.062,195.900300,195.900300,195.900300
XS GIS Cut Line= 6
1281757.39872363630726.0210924251281816.45339237 630622.72654519
 1281861.3089138630518.3301589871281935.25975519630223.854511201
1281970.09550327630119.9015990411282060.81419579629949.228609804
#Sta/Elev= 30
9580.093 106.5649601.177 101.5589620.405101.67789629.42399.590419650.697  96.677
9663.38893.78117 9717.2391.189399728.86991.820439742.58790.952079809.89690.40057
 9865.1891.496189912.74591.47625 9929.5690.758569949.73891.82389 9986.73 91.4684
10000.1990.4998210037.2292.4851610060.7992.3578510124.91 94.486110176.4497.60501
10216.91102.737310243.24107.095110268.28112.496910304.87121.9488 10315.9123.4947
10342.09131.671410361.26136.3979 10376.6141.800910403.45149.647910419.88155.8758
#Mann= 3 , 0 , 0
9580.093   0.045       09580.093   0.045       010419.88   0.045       0
#XS Ineff= 2 , 0
       09895.999        10092.49       0
Bank Sta=9580.093,10419.88
Exp/Cntr=0.3,0.1

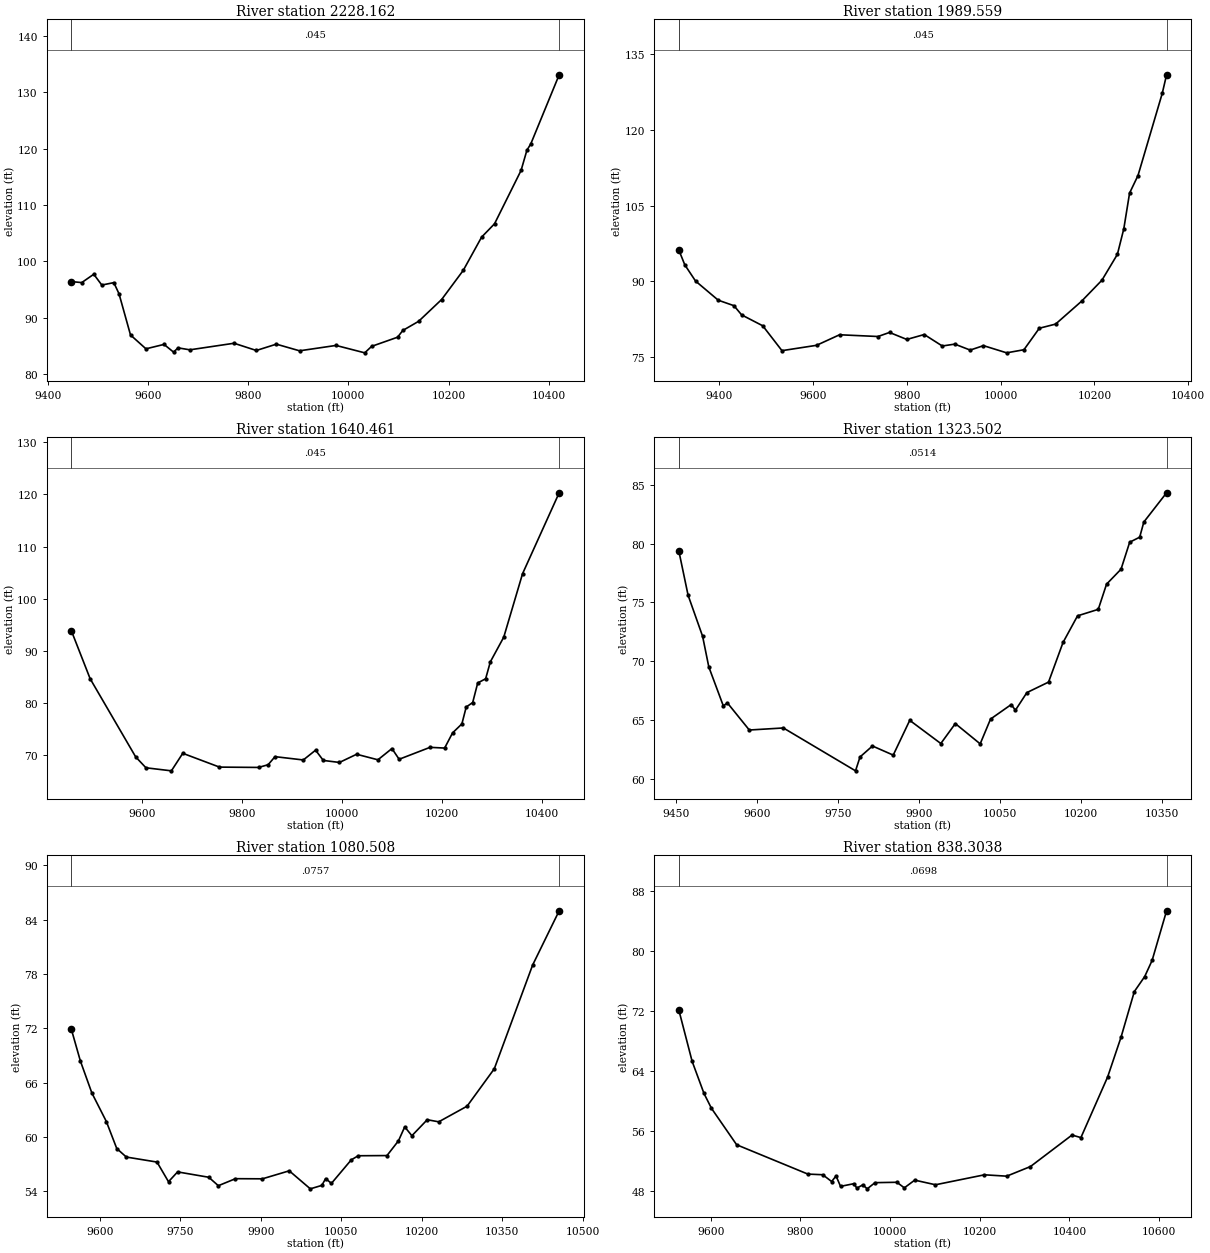
Type RM Length L Ch R = 1 ,2228.162,238.603400,238.603400,238.603400
XS GIS Cut Line= 6
1281833.59997195630866.044039547 1281960.7543236630684.305164605
1282040.82222238630545.2918828581282080.66377115630449.267168164
1282155.55446798630213.5046551971282270.64080793630004.384105995
#Sta/Elev= 30
9447.41896.413869468.08796.234889492.11197.715129508.12895.799579532.15396.22759
9542.51794.239129565.40986.942669596.21884.487099632.25685.272679651.25483.90537
9660.284 84.65729683.82984.312229771.982  85.4769816.41184.194459856.337 85.3156
9902.61184.135879975.41485.08992 10032.783.7761110046.3784.92406 10098.2 86.5486
10108.6187.7451310140.0889.3605310186.0593.2300710229.2498.4064210265.83   104.3
10291.68106.672210344.58116.133610356.18119.7041   10364120.843410420.58133.0923
#Mann= 3 , 0 , 0
9447.418   0.045       09447.418   0.045       010420.58   0.045       0
#XS Ineff= 2 , 0
       09875.844         10097.7       0
Bank Sta=9447.418,10420.58
Exp/Cntr=0.3,0.1

Type RM Length L Ch R = 1 ,1989.559,349.097500,349.097500,349.097500
XS GIS Cut Line= 2
1281909.98886088631018.8218173381282531.51663867630185.488483995
#Sta/Elev= 30
9314.15796.235089326.96393.276859349.88290.065659398.30286.268429431.73985.18253
9448.11183.362359493.13281.200569534.06176.278719607.732 77.33589656.846  79.425
9738.70379.08031 9763.2679.884749800.09678.497959837.31279.472939875.72677.20177
9902.41877.57288 9935.1676.392749963.52877.2710810012.9275.8466210049.7676.46172
 10082.5 80.716410117.1881.5374210172.5586.0642310215.9690.2297410248.8895.34391
10262.59100.422110274.87107.478410292.79 110.95210344.45127.210910353.74 130.908
#Mann= 3 , 0 , 0
9314.157   0.045       09314.157   0.045       010353.74   0.045       0
#XS Ineff= 2 , 0
       09824.014        10054.49       0
Bank Sta=9314.157,10353.74
Exp/Cntr=0.3,0.1

Type RM Length L Ch R = 1 ,1640.461,316.959600,316.959600,316.959600
XS GIS Cut Line= 6
1282069.71108311631143.8218173381282337.10059834630910.913000733
1282516.31110957630702.3564507661282581.04765353630636.274906814
1282668.43743786630561.2584959571282778.75104779630476.258771405
#Sta/Elev= 30
9458.10493.850799495.67584.658749586.88669.668759607.44367.583069658.38466.99854
9681.15370.359049754.684  67.7149832.80767.651279852.08968.169949865.815 69.7175
9922.52669.082749947.11170.959289962.56968.991889994.85668.6082910029.2870.17597
 10071.969.1142510099.9971.2704110114.3969.2168510176.2971.5038310205.4671.36325
10221.3574.2684310240.0575.99803 10248.779.2334110261.6780.0917910271.7283.84134
10287.6184.6517810296.9987.8887110323.8792.6244810361.49104.780910434.84120.3001
#Mann= 3 , 0 , 0
9458.104   0.045       09458.104   0.045       010434.84   0.045       0
#XS Ineff= 2 , 0
       09908.834        10037.23       0
Bank Sta=9458.104,10434.84
Exp/Cntr=0.3,0.1

Type RM Length L Ch R = 1 ,1323.502,242.993900,242.993900,242.993900
XS GIS Cut Line= 2
1282227.69719419631247.9884839951283000.26663867  630780.9745951
#Sta/Elev= 30
9455.43379.396639472.66975.612879499.50572.135439511.006 69.53169537.84266.22744
9545.50966.472239585.94364.177069649.01864.351389782.54460.713199790.86561.89093
9813.86762.821349852.306 62.04859882.87364.998289940.37863.031179967.21464.72295
10013.22 63.002910032.3965.1051310070.7266.3396510078.3965.8549510099.6467.35218
10139.73 68.242710166.5771.60788 10193.473.8648510231.7474.4158610247.0776.55148
10273.9177.82543 10289.980.1130510308.4180.5393810316.0881.8260410358.1984.30808
#Mann= 3 , 0 , 0
9455.433  0.0514       09455.433  0.0514       010358.19  0.0514       0
#XS Ineff= 2 , 0
       09903.989        10079.32       0
Bank Sta=9455.433,10358.19
Exp/Cntr=0.3,0.1

Type RM Length L Ch R = 1 ,1080.508,242.203900,242.203900,242.203900
XS GIS Cut Line= 2
1282305.82219419631383.4051506671283140.89163867631024.030150667
#Sta/Elev= 30
9547.04271.88103 9563.7768.39784  9585.2 64.86049612.22661.707799631.63358.72509
9649.49257.78442 9706.6457.23072 9728.0755.060989745.01956.145479803.11655.55387
9820.93554.622449852.91355.396949903.08655.38208 9953.0956.264389992.37954.27601
10013.8154.6564210020.9555.4105110031.67 54.8758 10068.757.4762110081.6757.92785
10135.2557.9478910156.6859.58039 10168.361.1136110181.6860.1384410210.2661.90371
10231.6961.6726810284.4963.3973210335.2767.52908 10406.778.9763710456.1684.96456
#Mann= 3 , 0 , 0
9547.042  0.0757       09547.042  0.0757       010456.16  0.0757       0
#XS Ineff= 2 , 0
       09959.095        10060.21       0
Bank Sta=9547.042,10456.16
Exp/Cntr=0.3,0.1

Type RM Length L Ch R = 1 ,838.3038,193.715400,193.715400,193.715400
XS GIS Cut Line= 2
 1282301.4819164631477.5891784281283380.04094422631334.360011771
#Sta/Elev= 30
9528.87272.13565 9558.6865.270739585.15760.992399601.70559.023829657.96954.16409
9816.83150.258939849.928 50.17389869.78549.271269879.714 50.00919889.643 48.6247
 9919.4348.981129926.04948.392269939.288 48.82499949.217 48.29559966.54449.11894
10015.4149.1694410031.96  48.42610055.1349.4545610101.4648.8378410210.6850.16408
10260.3249.9831410313.2851.2641910405.9555.45794 10425.855.1179610485.3863.18608
10515.1668.4584910544.9574.5634810568.1276.5638410584.6778.71935 10616.985.32189
#Mann= 3 , 0 , 0
9528.872  0.0698       09528.872  0.0698       0 10616.9  0.0698       0
#XS Ineff= 2 , 0
       09966.153        10069.07       0
Bank Sta=9528.872,10616.9
Exp/Cntr=0.3,0.1

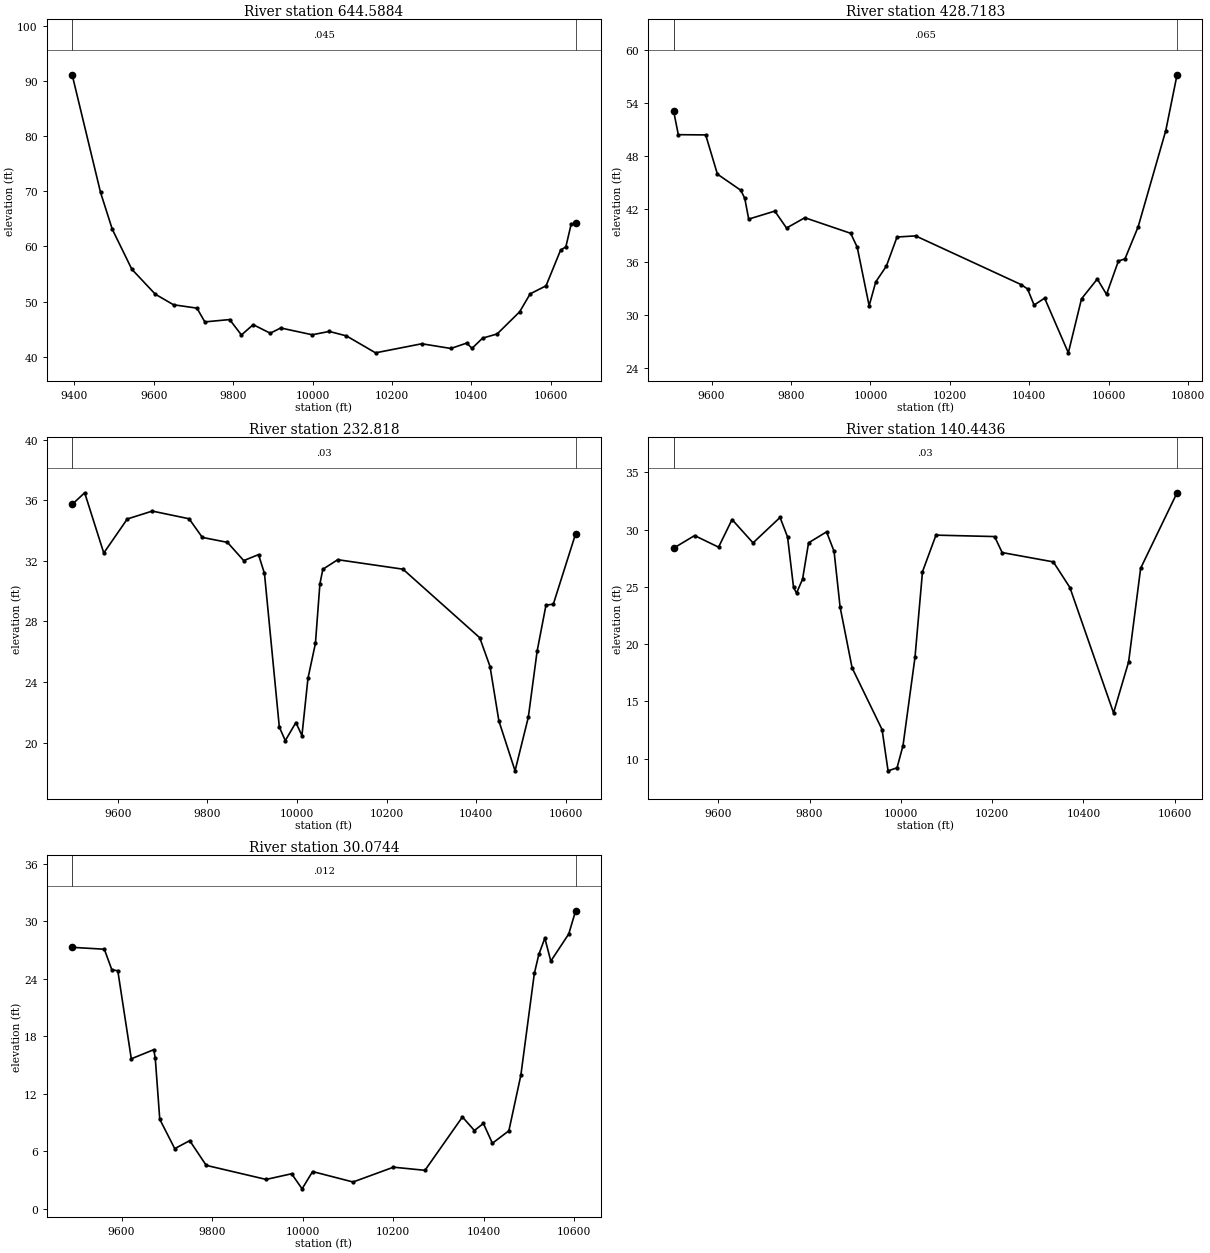
Type RM Length L Ch R = 1 ,644.5884,215.870100,215.870100,215.870100
XS GIS Cut Line= 6
1282210.65920368631575.3924218121282373.93608275631563.446921468
1282517.54689997 631566.139736221282687.41089737631581.714851052
1282870.00203648    631605.207581283467.45124513 631501.02378495
#Sta/Elev= 30
 9394.2491.178849465.70969.827069495.34463.123789544.60755.859939603.67651.33276
9649.61649.409139708.74148.794839728.48446.296529791.04746.720769820.72743.92232
9850.40845.793959893.32844.244139919.79445.191379999.19143.95937 10042.244.56592
 10085.443.7543510158.6740.6774510275.2342.3257610348.4941.4692410388.46 42.4523
10401.7841.4919710428.4243.3476510465.0644.1063310521.6748.1180710548.3251.39355
10588.2852.8505410624.91 59.328710638.2359.9364710651.5664.0455710662.8264.25038
#Mann= 3 , 0 , 0
 9394.24   0.045       0 9394.24   0.045       010662.82   0.045       0
#XS Ineff= 2 , 0
       09951.396        10021.54       0
Bank Sta=9394.24,10662.82
Exp/Cntr=0.3,0.1

Type RM Length L Ch R = 1 ,428.7183,195.900300,195.900300,195.900300
XS GIS Cut Line= 6
1282204.31743711631752.2579528991282368.95895454631750.585551426
1282473.43193316631755.0385864381282661.16108814631771.471650794
1282788.63180071631796.1626738161283461.46457127631894.344699368
#Sta/Elev= 30
9504.46253.080689516.34950.389729585.26850.362019614.80145.929439673.864 44.1013
9683.71543.182239693.56640.850729759.24341.753099788.82339.841769834.87541.00781
9950.22139.247199966.76437.678829996.78131.0547510013.49 33.759410040.19 35.5415
10066.9738.8259810113.6538.95603 10378.9 33.461410395.4832.9682310412.0531.13923
10438.5831.9198510498.2625.7398510531.4131.84271 10571.234.0841610594.4132.34457
10624.2536.1077610640.8336.3566710673.9839.9739310743.6150.8571710771.9857.15766
#Mann= 3 , 0 , 0
9504.462   0.065       09504.462   0.065       010771.98   0.065       0
#XS Ineff= 2 , 0
       09949.797        10063.56       0
Bank Sta=9504.462,10771.98
Exp/Cntr=0.3,0.1

Type RM Length L Ch R = 1 , 232.818,92.374400,92.374400,92.374400
XS GIS Cut Line= 6
 1282165.2896058631932.6739944961282332.11706072631933.861461431
1282507.65936434631946.1102076621282799.13429794631993.546558663
1282978.74328011632015.8497068141283282.91276136632035.213599741
#Sta/Elev= 30
9497.95235.737069525.89936.50326 9568.5532.523619621.05334.771869676.85935.29371
9759.02134.786849788.65433.554559844.64433.228179881.03432.022689914.11532.41761
9927.348  31.1729960.51321.025799973.85320.129829997.52821.3242210011.0120.46182
10024.4824.2450210041.1626.5556610051.12  30.48210057.7631.4508410090.9532.08253
10236.5931.4557110407.9926.92755   1043125.0248810450.73 21.435310486.8918.13343
10516.4821.67334 10536.226.0474410555.9329.0763110572.3629.1479410622.1233.79453
#Mann= 3 , 0 , 0
9497.952    0.03       09497.952    0.03       010622.12    0.03       0
#XS Ineff= 2 , 0
       09888.541        10091.02       0
Bank Sta=9497.952,10622.12
Exp/Cntr=0.3,0.1

Type RM Length L Ch R = 1 ,140.4436,110.369200,110.369200,110.369200
XS GIS Cut Line= 6
1282163.59431896632039.1922864171282330.72735018632043.960185751
1282581.00502917632061.7928470081282706.53922379 632062.45540534
1282757.44049811632064.8157223611283263.38151136632117.678877518
#Sta/Elev= 30
9501.91128.374769547.96329.473899600.46428.462639630.02230.87236 9676.0128.83595
9735.21531.05652 9751.6629.351379764.817 24.94379771.39524.456399784.55225.67095
9797.70828.842529837.178 29.79829853.62428.093249866.78123.243699893.09417.93084
 9958.7812.544149971.9048.942855 9991.599.20656410004.7111.1539510030.9618.85479
10047.3726.3211210076.9329.5115910205.4129.3876210221.9127.9916210334.0927.17628
10370.3824.9407810466.0613.9978810499.06 18.449710525.4526.6221310605.2333.20773
#Mann= 3 , 0 , 0
9501.911    0.03       09501.911    0.03       010605.23    0.03       0
#XS Ineff= 2 , 0
       09873.239        10071.32       0
Bank Sta=9501.911,10605.23
Exp/Cntr=0.3,0.1

Type RM Length L Ch R = 1 , 30.0744,0.000000,0.000000,0.000000
XS GIS Cut Line= 2
1282145.75998357632102.4879052941283248.19053912632250.057349741
#Sta/Elev= 30
9490.82527.294369561.89527.098229578.44524.957069591.68624.843129621.47615.65105
9671.12816.602679674.43815.719989684.3689.3325549717.4696.264492 9750.577.101259
9786.9814.5195019919.3853.0486849975.6573.6409869998.8272.065868   100223.871509
10111.372.78023110200.744.32816310270.264.00015510353.019.57455710379.498.159243
10399.358.89774110419.216.82734610455.628.131318 10482.113.9356410511.8924.56919
10521.8226.5524310535.0628.25335 10548.325.8527710588.0228.7020610603.0931.11359
#Mann= 3 , 0 , 0
9490.825   0.012       09490.825   0.012       010603.09   0.012       0
#XS Ineff= 2 , 0
       0 9881.61        10059.75       0
Bank Sta=9490.825,10603.09
Exp/Cntr=0.3,0.1